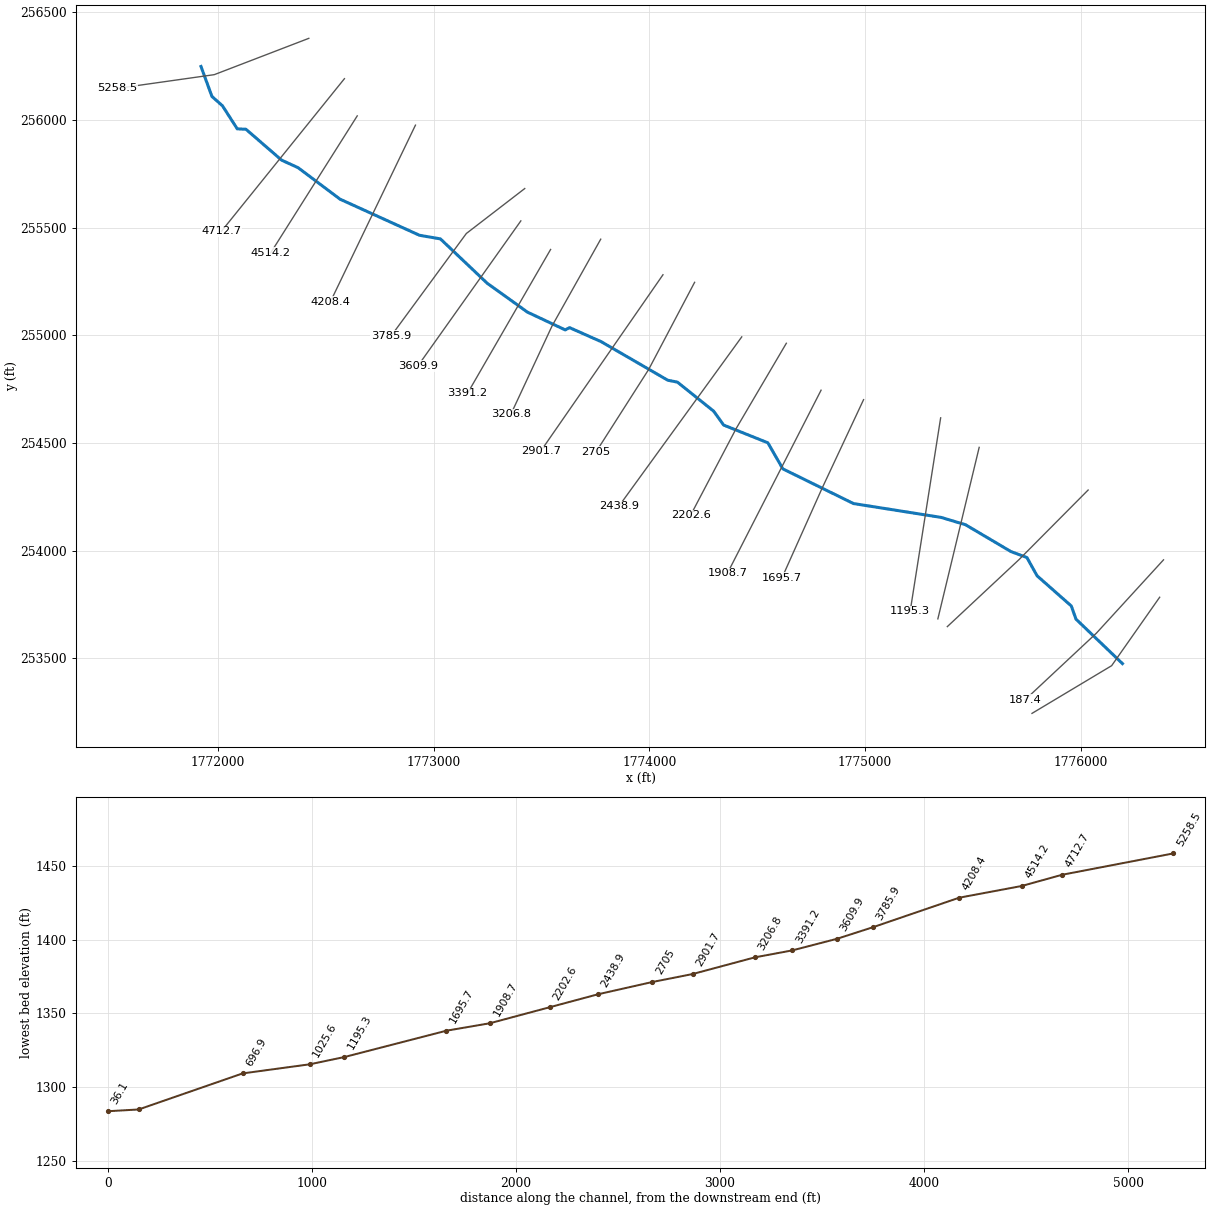
--- LowerRdBr.prj (project) ---

Proj Title=LowerRdBr
Current Plan=p01
Default Exp/Contr=0,0
English Units
Geom File=g01
Flow File=f01
Plan File=p01
BEGIN DESCRIPTION:
END DESCRIPTION:
DSS Export Rating Curves= 0
DSS Export Rating Curve Sorted= 0
DSS Export Volume Flow Curves= 0
DXF OffsetX= 0
DXF OffsetY= 0
DXF ScaleX= 0
DXF ScaleY= 0

--- LowerRdBr.p01 (plan) ---

Plan Title=Floodplain
Program Version=4.00
Geom File=g01
Flow File=f01
K Sum by GR=0
Std Step Tol=0.01
Critical Tol=0.01
Num of Std Step Trials=20
Max Error Tol=0.3
Flow Tol Ratio=0.001
Split Flow NTrial=30
Split Flow Tol=0.02
Split Flow Ratio=0.02
Log Output Level=0
Friction Slope Method=1
Unsteady Friction Slope Method=2
Unsteady Bridges Friction Slope Method=1
Global Log Level=0
CheckData=False
Run HTab=0
Run UNet=0
Run PostProcess=0
UNET Theta=0
UNET Theta Warmup=0
UNET ZTol=0
UNET ZSATol=0
UNET MxIter=0
UNET MaxInSteps=0
UNET DtIC=0
UNET DtMin=0
UNET MaxCRTS=0
UNET WFStab=0
UNET SFStab=0
UNET WFX=0
UNET SFX=0
UNET DSS MLevel=0
UNET DZMax Abort=0
UNET Convert EG Bridges=0
UNET Use Existing IB Tables=0
UNET Froude Limit=0
UNET Froude Power=0
Write IC File=0
Echo Input=False
Echo Output=False
Write Detailed=0

--- LowerRdBr.f01 (steady flow) ---

Flow Title=NFF Regression Equation
Program Version=4.00
Number of Profiles=1
Profile Names=P100yr
River Rch & RM=LowerRdBr,Main      ,5258.5
639.8080
River Rch & RM=LowerRdBr,Main      ,4514.2
653.4616
River Rch & RM=LowerRdBr,Main      ,4208.4
715.4627
River Rch & RM=LowerRdBr,Main      ,2202.6
777.3950
River Rch & RM=LowerRdBr,Main      ,1908.7
885.6700
River Rch & RM=LowerRdBr,Main      ,187.4
955.4826
Boundary for River Rch & Prof#=LowerRdBr,Main      ,1
Up Type=0
Dn Type=3
Dn Slope=0.02496

--- LowerRdBr.g01 (geometry) ---

Geom Title=USGS 10m DEM
Program Version=4.00

River Reach=LowerRdBr       ,Main
Reach XY= 30
     1771921.409      256249.082     1771972.185      256109.884
     1772021.211      256066.111     1772089.497      255959.305
     1772129.768      255957.554      1772295.23      255813.979
     1772371.501      255778.877     1772565.746      255632.758
     1772934.431      255464.881     1773031.491      255448.037
     1773248.019       255242.25      1773434.93      255107.793
     1773610.169       255025.19     1773630.305      255035.695
     1773776.348      254970.793     1774085.543      254791.443
     1774130.191      254782.688     1774298.415      254647.527
     1774344.679      254583.083     1774549.536       254500.79
     1774619.089      254379.578     1774946.677      254218.377
     1775353.353      254153.983     1775466.142      254119.966
     1775676.358      253995.513     1775750.666      253967.635
     1775797.941      253882.716     1775956.399      253742.643
     1775978.285       253681.36     1776193.648      253474.752

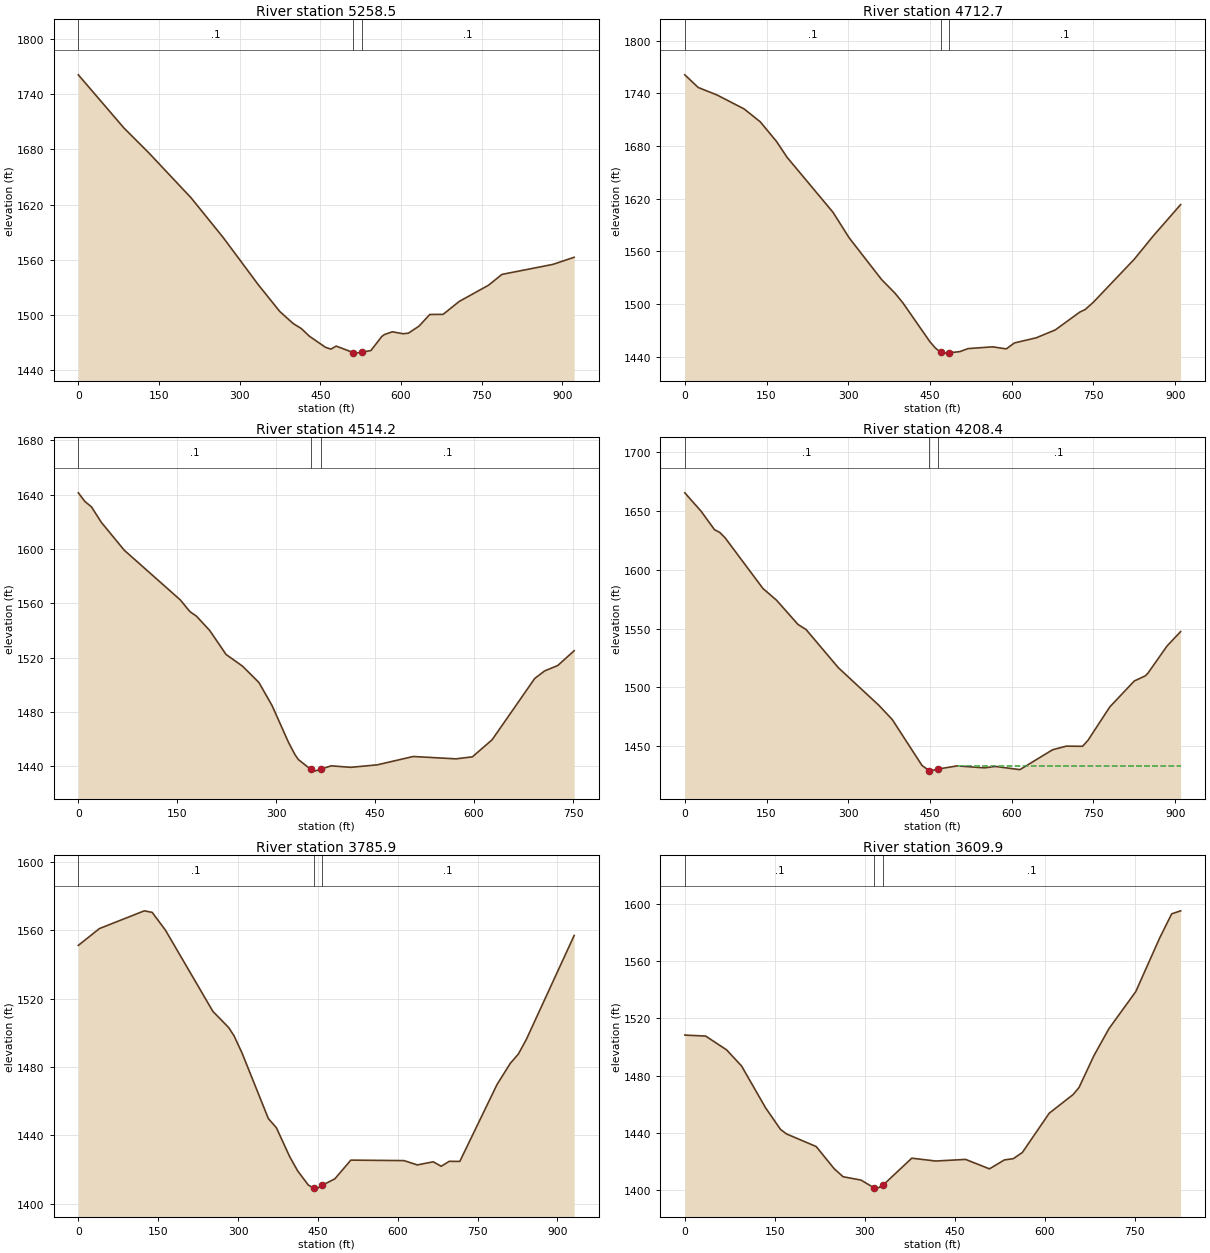
Type RM Length L Ch R = 1 ,5258.5  ,527.9,545.7,563.6
XS GIS Cut Line= 3
     1772421.347      256379.862     1771983.191      256211.157
      1771535.23      256147.662
#Sta/Elev= 30
       0 1760.78    84.9 1703.02   129.9 1676.82   209.8 1627.22   269.7 1583.98
   334.6 1533.01   374.6 1503.96   399.6 1490.83   414.6 1485.45   429.6 1477.15
   459.5 1465.12   469.5 1463.08   479.5 1466.38   511.6 1459.25   514.3 1458.75
   526.6 1459.64   544.1 1461.58     564 1476.65     569 1478.88   583.9 1481.91
   603.8  1479.8   613.7 1480.37   633.6 1488.08   653.5  1500.7   678.3 1500.82
   708.2  1514.8   762.8 1532.47   787.7 1544.19   882.2 1555.02     922 1562.78
#Mann= 3 , 0 , 0
       0      .1       0   511.6    .045       0   526.6      .1       0
Bank Sta=511.6,526.6
XS Rating Curve= 0 ,0
Exp/Cntr=0.3,0.1

Type RM Length L Ch R = 1 ,4712.7  ,196,198.6,201.1
XS GIS Cut Line= 3
     1772586.495      256192.463      1772301.32      255837.921
     1772016.145      255483.378
#Sta/Elev= 30
       0 1761.19    24.7 1746.75    59.4 1738.17   108.8 1722.38   138.5 1707.68
   168.2 1685.43   187.9 1667.14     272 1604.62   301.7 1575.52     361 1528.16
   385.8 1512.49   400.6 1501.19     450 1457.12     460 1449.97   469.5 1445.21
     475 1444.22   484.5 1444.46     505    1446     520 1449.39     565 1451.39
     590 1449.05     605 1455.83     645 1461.67     680 1470.67     725 1490.98
     735 1493.94     750  1502.3     825 1551.22     860 1577.87     910 1613.39
#Mann= 3 , 0 , 0
       0      .1       0   469.5    .045       0   484.5      .1       0
Bank Sta=469.5,484.5
XS Rating Curve= 0 ,0
Exp/Cntr=0.3,0.1

Type RM Length L Ch R = 1 ,4514.2  ,303.1,305.7,308.4
XS GIS Cut Line= 2
     1772645.844      256019.575     1772244.858      255383.616
#Sta/Elev= 30
       0 1641.28      10 1634.91    19.9 1630.97    34.8 1619.63    69.7 1599.04
   154.4 1562.62   169.3 1553.86   179.2 1550.52   199.2 1540.05     224 1522.39
     249 1513.78   273.8 1501.78   293.8 1484.76   318.6 1457.83   328.6 1448.61
   333.6 1445.12   352.6 1437.84   358.5 1436.58   367.6 1438.06   383.4 1440.46
   413.2 1439.38   453.1 1441.19   507.8 1447.34   572.6 1445.61   597.5 1447.09
   627.4 1459.65   692.1 1504.79     707 1510.28   726.9 1514.25   751.8 1525.13
#Mann= 3 , 0 , 0
       0      .1       0   352.6    .045       0   367.6      .1       0
Bank Sta=352.6,367.6
XS Rating Curve= 0 ,0
Exp/Cntr=0.3,0.1

Type RM Length L Ch R = 1 ,4208.4  ,427.1,422.6,418
XS GIS Cut Line= 3
     1772915.774      255976.536     1772718.707      255566.427
     1772521.641      255156.317
#Sta/Elev= 30
       0 1665.49    29.7 1649.97    54.4 1634.19    64.3 1631.73    74.2 1627.08
   143.4  1584.1   168.2 1574.18   207.7  1553.5   222.6 1549.13   281.9 1516.62
   356.1 1484.69   380.8 1472.53   435.2 1433.57     449 1428.83     450 1428.64
     464 1430.36     500  1433.1     550 1431.43     570 1432.63     615 1429.91
     675 1446.82     700  1449.9     730 1449.77     740 1454.87     780 1483.28
     825 1505.38     845 1509.69     850 1511.99     885 1535.09     910 1547.39
#Mann= 3 , 0 , 0
       0      .1       0     449    .045       0     464      .1       0
#XS Ineff= 2 , 0
                          500.95         1433.17
Permanent Ineff=
       F       F
Bank Sta=449,464
XS Rating Curve= 0 ,0
Exp/Cntr=0.3,0.1

Type RM Length L Ch R = 1 ,3785.9  ,175.6,175.9,176.3
XS GIS Cut Line= 3
     1773422.475      255681.965     1773151.546      255473.008
      1772803.18      254997.481
#Sta/Elev= 30
       0 1551.27    39.7 1561.12     124  1571.5   138.8 1570.58   163.6 1560.22
   252.9  1512.6   282.6 1503.13   292.6 1498.31   307.4 1488.41   357.1 1449.86
   372.1 1444.53   397.1 1427.61   412.1 1419.26   432.1 1410.98   443.1 1409.02
   447.1 1408.58   458.1  1410.8     482 1414.61     512 1425.56   611.9 1425.28
   636.9 1422.75   666.9 1424.58   681.8 1421.96   696.8 1424.85   716.8 1424.83
   786.8 1469.89   811.7 1482.25   826.7 1487.63   841.7 1496.18   931.6 1557.05
#Mann= 3 , 0 , 0
       0      .1       0   443.1    .045       0   458.1      .1       0
Bank Sta=443.1,458.1
XS Rating Curve= 0 ,0
Exp/Cntr=0.3,0.1

Type RM Length L Ch R = 1 ,3609.9  ,216.6,218.7,220.8
XS GIS Cut Line= 2
     1773404.397      255531.751     1772926.789      254857.481
#Sta/Elev= 30
       0 1508.32    34.8 1507.64    69.7 1497.98    94.6 1486.74   134.4 1457.66
   159.3 1442.54   169.2 1439.33     219 1430.46   248.9 1414.99   263.8 1409.37
   293.7 1407.03   315.3 1401.64   318.6 1400.71   330.3 1403.46   378.3 1422.34
   418.1 1420.34   467.9 1421.48   507.7 1414.88   532.6 1421.11   547.5 1422.01
   562.5 1426.28   607.3 1453.74   647.1 1466.77     657 1471.71   681.9 1494.02
   706.8 1512.78   751.6 1538.74   791.4 1576.17   811.4 1593.01   826.3 1595.13
#Mann= 3 , 0 , 0
       0      .1       0   315.3    .045       0   330.3      .1       0
Bank Sta=315.3,330.3
XS Rating Curve= 0 ,0
Exp/Cntr=0.3,0.1

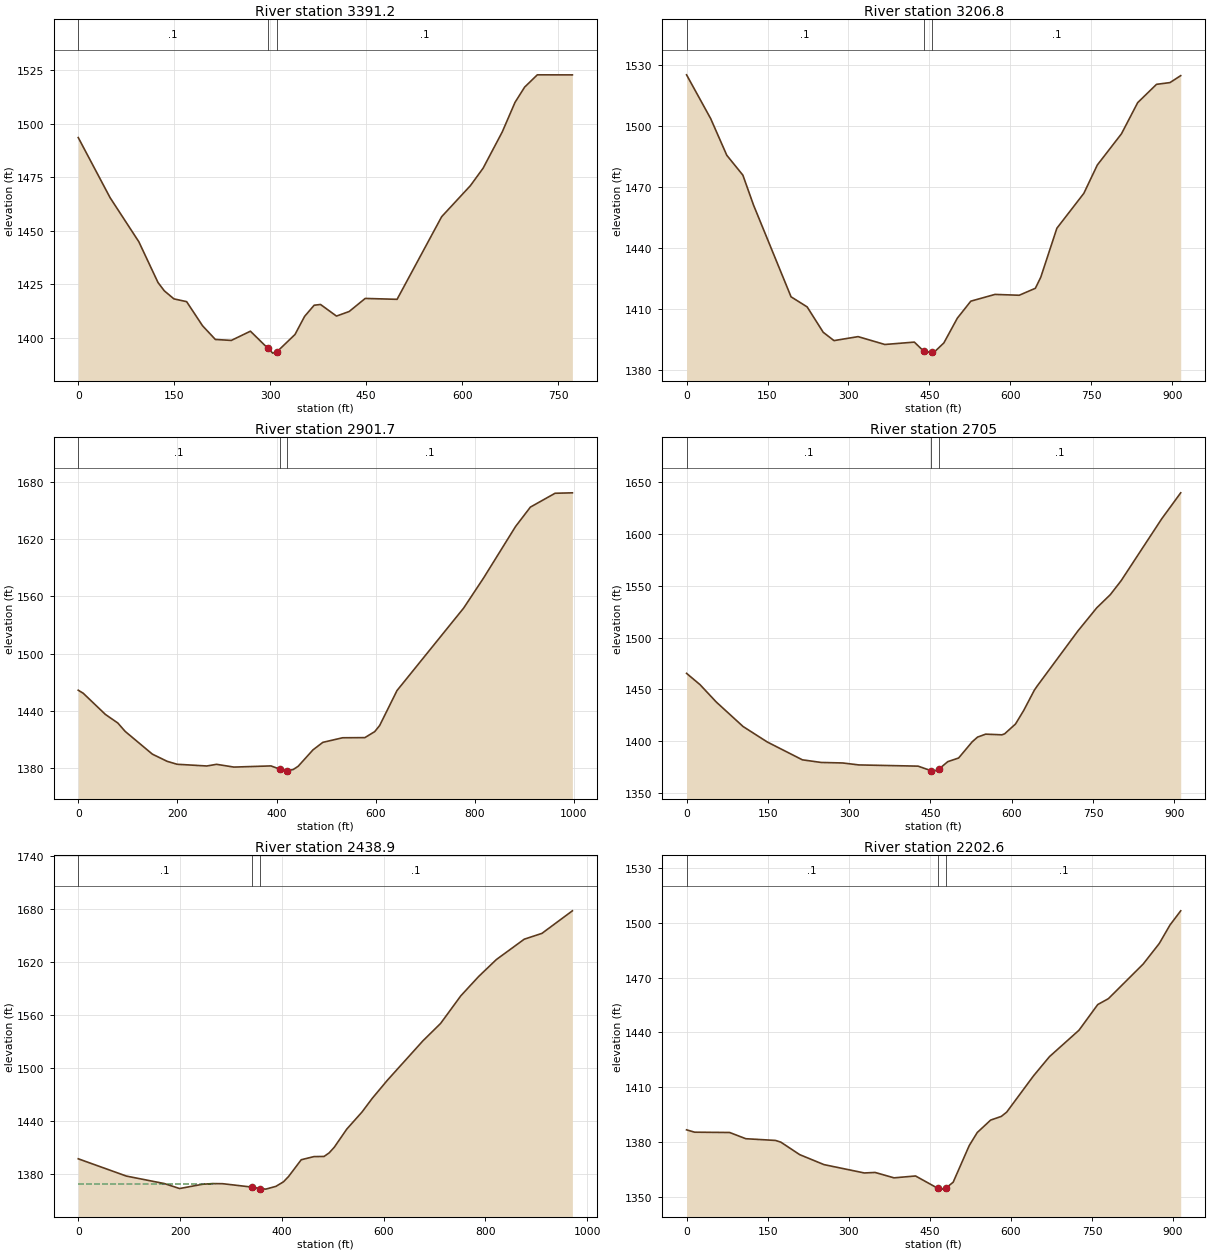
Type RM Length L Ch R = 1 ,3391.2  ,184.1,184.4,185.2
XS GIS Cut Line= 2
     1773542.316       255398.94     1773156.654      254729.779
#Sta/Elev= 30
       0 1493.62    49.8  1465.5    94.7  1444.9   124.6 1425.88   134.5 1421.97
   149.5 1418.21   169.4  1416.9   194.3 1405.62   214.3 1399.23   239.2 1398.78
   269.1 1403.09   295.9 1395.23     304 1392.84   310.9 1393.56   338.8 1401.57
   353.8 1410.03   368.7 1415.23   378.7 1415.58   403.6 1410.16   423.5 1412.31
   448.5 1418.41   498.3 1417.99     568 1456.63   612.9 1471.13   632.8 1479.32
   662.7 1496.26   682.6 1510.05   697.6 1517.18   717.5 1522.95   772.3 1522.92
#Mann= 3 , 0 , 0
       0      .1       0   295.9    .045       0   310.9      .1       0
Bank Sta=295.9,310.9
XS Rating Curve= 0 ,0
Exp/Cntr=0.3,0.1

Type RM Length L Ch R = 1 ,3206.8  ,306.7,305.1,302.3
XS GIS Cut Line= 3
     1773774.723      255446.684     1773549.187      255043.785
     1773357.702      254632.349
#Sta/Elev= 30
       0 1524.93    44.7 1503.39    74.5 1485.38   104.3 1475.61   124.1 1460.85
   193.6 1415.77   223.4 1410.81   253.2 1398.32   273.1 1394.24   317.8 1396.19
   367.4 1392.33     422  1393.5   439.6 1388.97   454.6 1388.39   456.8 1388.08
   476.7  1393.1   501.6 1405.24   526.6 1413.63   571.4 1416.95   616.3 1416.54
   646.2 1419.96   656.2 1425.37   686.1  1449.5     736 1466.64     761 1480.59
   805.8 1495.96   835.8 1511.26   870.7 1520.26   895.6 1521.11   915.5 1524.53
#Mann= 3 , 0 , 0
       0      .1       0   439.6    .045       0   454.6      .1       0
Bank Sta=439.6,454.6
XS Rating Curve= 0 ,0
Exp/Cntr=0.3,0.1

Type RM Length L Ch R = 1 ,2901.7  ,194.1,196.7,197.5
XS GIS Cut Line= 2
     1774063.343      255281.454     1773496.343      254461.603
#Sta/Elev= 30
       0 1461.58      10 1458.43    54.8  1436.2    79.8 1427.21    94.7 1418.39
   149.5 1394.56   179.4 1387.01   199.4 1383.94   259.2 1382.13   279.1 1383.87
     314 1380.98   388.8 1382.21   406.9 1378.73   418.7 1376.74   421.9 1377.14
   433.6 1378.42   443.6  1381.8   473.5 1399.03   493.4 1406.91   533.3 1411.73
   578.2 1411.88   598.1 1418.19   608.1 1424.65     643 1461.24   777.5 1547.78
   817.4  1579.1   882.2 1633.32   912.1 1653.66   961.9 1668.16   996.8 1668.62
#Mann= 3 , 0 , 0
       0      .1       0   406.9    .045       0   421.9      .1       0
Bank Sta=406.9,421.9
XS Rating Curve= 0 ,0
Exp/Cntr=0.3,0.1

Type RM Length L Ch R = 1 ,2705    ,269.4,266.1,264.5
XS GIS Cut Line= 3
     1774210.009      255246.297     1773997.317      254841.918
      1773753.08      254458.423
#Sta/Elev= 30
       0 1465.47    24.8 1454.62    54.6 1437.98   104.3 1414.27     149 1399.36
   213.6 1382.23   248.3 1379.69     288  1379.2   317.8 1377.31   427.1 1376.14
   451.1 1371.75   456.9 1371.34   466.1 1373.58   481.9 1380.47   501.9 1383.98
   526.8 1399.49   536.8  1404.1   551.8 1406.94   581.8  1406.3   586.8 1407.27
   606.8 1416.69   621.8 1429.61   641.8 1449.48   646.8 1453.24   721.7 1506.12
   756.7 1528.57   781.7 1541.24   801.6 1554.63   876.6 1614.32   911.6  1639.3
#Mann= 3 , 0 , 0
       0      .1       0   451.1    .045       0   466.1      .1       0
Bank Sta=451.1,466.1
XS Rating Curve= 0 ,0
Exp/Cntr=0.3,0.1

Type RM Length L Ch R = 1 ,2438.9  ,233.5,236.3,239.6
XS GIS Cut Line= 2
     1774428.572      254992.846     1773859.018      254206.198
#Sta/Elev= 30
       0 1397.32    94.6 1377.77   169.3 1369.29   199.2 1363.67     244 1368.48
     264 1369.27   283.9 1369.14   341.6  1365.3   356.6 1363.66   368.6 1363.01
   388.5 1366.14   403.4  1371.3   413.4  1377.3   438.3 1396.25   463.2 1399.79
   483.1 1399.97   493.1 1403.97     503 1410.22   527.9 1430.98   557.8 1450.27
   577.7 1465.57   607.6 1486.17   677.3 1530.65   712.2 1550.41     752  1581.7
   786.9 1603.46   821.8 1622.66   876.6 1645.68   911.4 1652.28   971.2 1677.77
#Mann= 3 , 0 , 0
       0      .1       0   341.6    .045       0   356.6      .1       0
#XS Ineff= 2 , 0
          271.26 1369.24
Permanent Ineff=
       F       F
Bank Sta=341.6,356.6
XS Rating Curve= 0 ,0
Exp/Cntr=0.3,0.1

Type RM Length L Ch R = 1 ,2202.6  ,308.3,293.9,296.2
XS GIS Cut Line= 3
     1774635.271      254963.132     1774403.142       254567.75
      1774191.52      254164.316
#Sta/Elev= 30
       0 1386.68      15 1385.39    79.7 1385.23   109.6 1381.82   164.5 1380.88
   174.4 1379.94   209.3  1373.1   254.2 1367.64   328.9 1363.07   348.8 1363.35
   383.7  1360.4   423.6 1361.42   464.7 1354.68   473.3 1354.22   479.7 1354.75
   493.2 1358.02   522.9 1378.07   537.7 1385.21   562.5 1392.02   582.3 1394.05
   592.2 1396.39   641.7  1416.2   671.4 1426.78   725.9 1441.22   760.6 1455.27
   780.4 1458.52   844.7 1477.47   874.4 1488.69   894.2  1498.8   914.1  1506.6
#Mann= 3 , 0 , 0
       0      .1       0   464.7    .045       0   479.7      .1       0
Bank Sta=464.7,479.7
XS Rating Curve= 0 ,0
Exp/Cntr=0.3,0.1

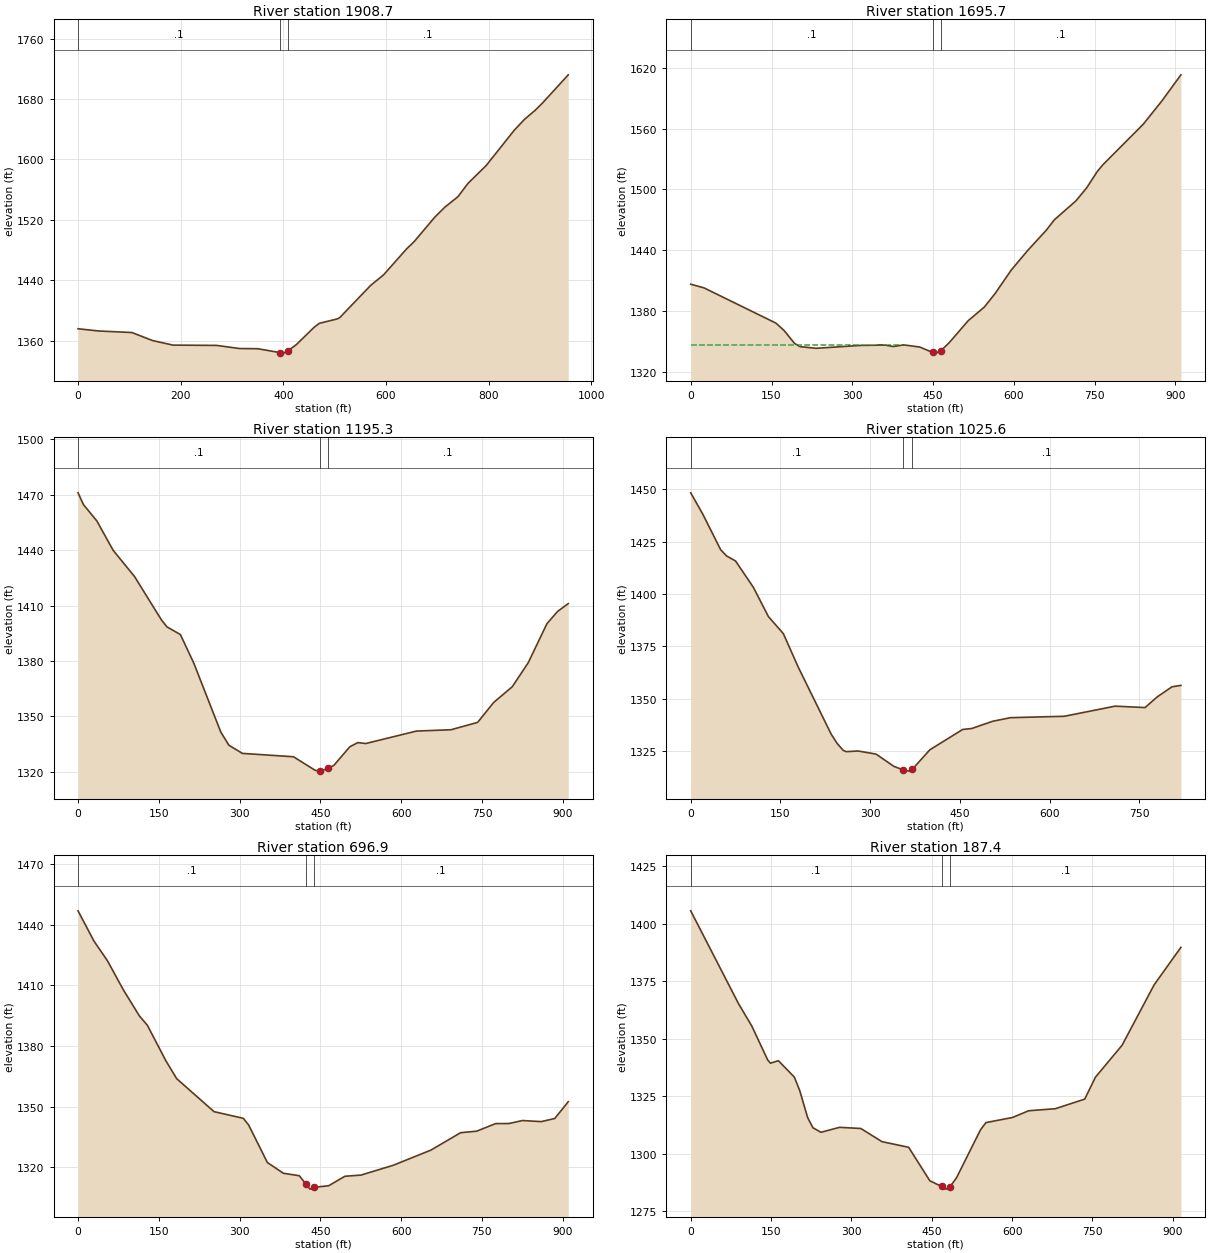
Type RM Length L Ch R = 1 ,1908.7  ,213.2,213,213.2
XS GIS Cut Line= 2
     1774796.355      254745.103     1774362.166      253894.604
#Sta/Elev= 30
       0 1375.62      40 1372.66     105  1370.6     145    1360     185 1353.93
     270 1353.53     315 1349.37     350 1349.16   393.5 1343.99     400  1343.3
   408.5 1346.28     425 1354.41     460 1377.64     470  1382.8     505 1388.67
     510 1390.51     570 1433.09     595 1446.96     640 1481.47   654.9 1491.26
   694.9 1523.53   714.9 1537.02   739.9 1550.59   759.9 1568.56   794.9 1591.89
   849.9 1638.93   869.9 1653.36   889.9 1664.89   904.9 1674.98   954.9 1712.25
#Mann= 3 , 0 , 0
       0      .1       0   393.5    .045       0   408.5      .1       0
Bank Sta=393.5,408.5
XS Rating Curve= 0 ,0
Exp/Cntr=0.3,0.1

Type RM Length L Ch R = 1 ,1695.7  ,494,500.4,506.3
XS GIS Cut Line= 3
     1774993.409       254701.15     1774800.717      254288.878
     1774615.159       253873.45
#Sta/Elev= 30
       0 1406.32    24.7 1402.68   158.3 1367.86   173.1 1360.72   192.9 1347.81
   202.8 1344.67   232.5    1343   316.6  1345.9   361.1 1346.15   375.9 1344.75
   395.7 1346.34   425.4 1344.24   449.1 1338.91   455.1 1338.23   464.1 1340.37
   480.1 1348.62   515.1 1370.22   545.1 1383.72   565.1 1397.08   595.1 1420.24
   625.1  1439.3   660.1 1459.59   675.1  1469.9   715.1 1488.57   735.1 1501.46
   755.1 1517.79   765.1  1524.2   840.1 1564.27   875.1 1587.53   910.1 1613.11
#Mann= 3 , 0 , 0
       0      .1       0   449.1    .045       0   464.1      .1       0
#XS Ineff= 2 , 0
          395.25 1346.33
Permanent Ineff=
       F       F
Bank Sta=449.1,464.1
XS Rating Curve= 0 ,0
Exp/Cntr=0.3,0.1

Type RM Length L Ch R = 1 ,1195.3  ,171.5,169.7,167.9
XS GIS Cut Line= 3
     1775350.736      254616.635     1775280.064      254167.158
     1775209.391       253717.68
#Sta/Elev= 30
       0 1471.05      10  1464.7      35 1455.79      65 1439.99     105 1425.66
     155 1402.13     165 1398.46     190  1394.3     215 1378.73     265 1341.48
     280 1334.37     305 1329.93     400  1328.1     440 1320.79   448.6 1320.34
     450 1320.32   463.6 1321.81   474.8  1323.4   504.5  1333.5   519.3 1335.77
   534.1 1335.27   628.1 1342.01   692.4 1342.74   741.8 1346.72   771.5 1357.49
   806.1 1366.04   835.8 1379.08   870.4 1400.15   890.2 1406.81     910 1411.04
#Mann= 3 , 0 , 0
       0      .1       0   448.6    .045       0   463.6      .1       0
Bank Sta=448.6,463.6
XS Rating Curve= 0 ,0
Exp/Cntr=0.3,0.1

Type RM Length L Ch R = 1 ,1025.6  ,342.2,328.7,316.1
XS GIS Cut Line= 2
     1775529.368      254479.482     1775337.814      253682.618
#Sta/Elev= 30
       0 1448.28      20 1438.21      50 1421.16      60 1418.14      75 1415.73
   104.9  1403.1   129.9  1389.2   154.9 1381.04   179.9 1364.99   234.9 1333.03
   244.9  1328.6   254.9 1325.33   259.9 1324.69   279.8    1325   309.8 1323.54
   339.8 1317.65   355.2    1316   364.8 1315.39   370.2 1316.17   399.8 1325.57
   454.8  1335.3   469.8 1335.73   504.7 1339.18   534.7 1340.91   624.7 1341.58
   709.6 1346.42   759.6 1345.74   779.6 1350.75   804.6 1355.65   819.6 1356.33
#Mann= 3 , 0 , 0
       0      .1       0   355.2    .045       0   370.2      .1       0
Bank Sta=355.2,370.2
XS Rating Curve= 0 ,0
Exp/Cntr=0.3,0.1

Type RM Length L Ch R = 1 ,696.9   ,509.4,509.6,509.2
XS GIS Cut Line= 3
     1776034.444      254281.234      1775713.75      253957.633
     1775381.709      253646.669
#Sta/Elev= 30
       0 1446.78    29.7 1431.77    54.5 1422.16    84.2  1407.7   113.9 1394.85
   128.8 1390.18   163.4 1372.53   183.2 1363.81   252.6  1347.5     307  1344.2
   316.9  1340.9   351.6 1322.37   381.3 1317.05     411 1315.82     423 1311.78
   430.8  1309.2     438 1310.08   465.6 1310.88   495.6 1315.55   525.6 1316.15
   585.6    1321   655.6 1328.51   710.5 1337.09   740.5 1337.85   775.5 1341.59
   800.5 1341.63   825.5 1343.11   860.5 1342.57   885.5 1344.13   910.5 1352.41
#Mann= 3 , 0 , 0
       0      .1       0     423    .045       0     438      .1       0
Bank Sta=423,438
XS Rating Curve= 0 ,0
Exp/Cntr=0.3,0.1

Type RM Length L Ch R = 1 ,187.4   ,147.2,151.3,155.9
XS GIS Cut Line= 3
      1776384.03      253956.906     1776072.895      253616.299
      1775741.73      253306.128
#Sta/Elev= 30
       0 1405.59    89.3 1365.24   114.1 1355.52   143.8 1340.76   148.8  1339.4
   163.7 1340.49   193.5 1333.35   203.4 1327.59   218.3 1315.75   228.2 1311.35
   243.1 1309.38   277.8 1311.53   317.5 1311.04   357.2  1305.3   406.8 1302.88
   446.4 1288.33   468.4 1285.85   476.3 1284.69   483.4  1285.5   496.2 1289.62
   541.1 1310.48   551.1 1313.59   600.9 1315.82   630.8 1318.73   680.7 1319.62
   735.6  1323.8   755.5  1333.3   805.4 1347.23   865.2 1373.47   915.1 1389.72
#Mann= 3 , 0 , 0
       0      .1       0   468.4    .045       0   483.4      .1       0
Bank Sta=468.4,483.4
XS Rating Curve= 0 ,0
Exp/Cntr=0.3,0.1

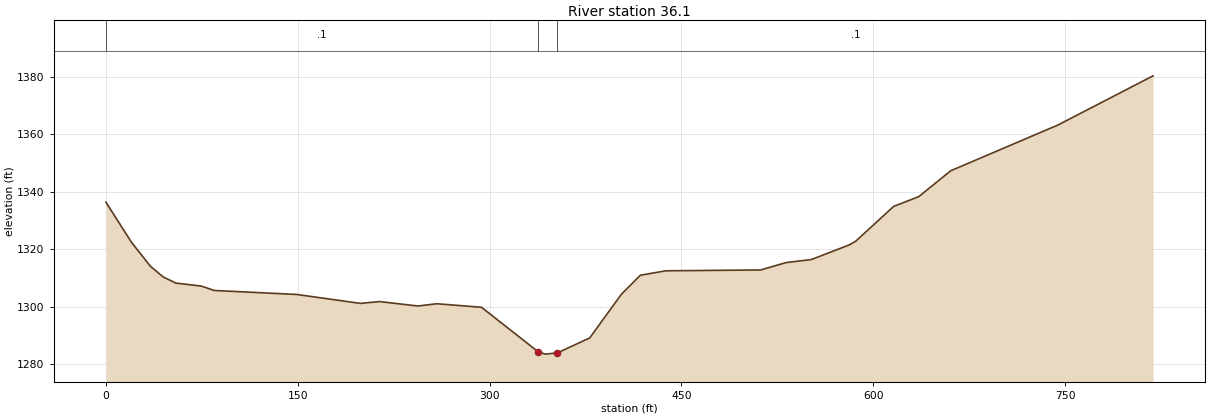
Type RM Length L Ch R = 1 ,36.1    ,40.6,36.1,31.6
XS GIS Cut Line= 3
     1776366.162       253783.19     1776143.498      253465.099
     1775774.286      253243.572
#Sta/Elev= 30
       0 1336.42    19.9 1322.51    34.8 1314.08    44.8 1310.36    54.8 1308.22
    74.7 1307.18    84.6 1305.66   149.3 1304.26   199.1 1301.15     214 1301.79
   243.9 1300.25   258.8 1301.03   293.7  1299.8   338.1 1284.27   343.5 1283.49
   353.1 1283.93   378.3 1289.12   403.1 1304.34     418 1310.98   437.8  1312.5
     512  1312.8   531.8 1315.36   551.6 1316.42   581.3 1321.53   586.2 1322.76
   615.9  1334.9   635.7 1338.35   660.5 1347.31   744.6  1363.3   818.8 1380.39
#Mann= 3 , 0 , 0
       0      .1       0   338.1    .045       0   353.1      .1       0
Bank Sta=338.1,353.1
XS Rating Curve= 0 ,0
Exp/Cntr=0.3,0.1

Chan Stop Cuts=-1
Use User Specified Reach Order=0